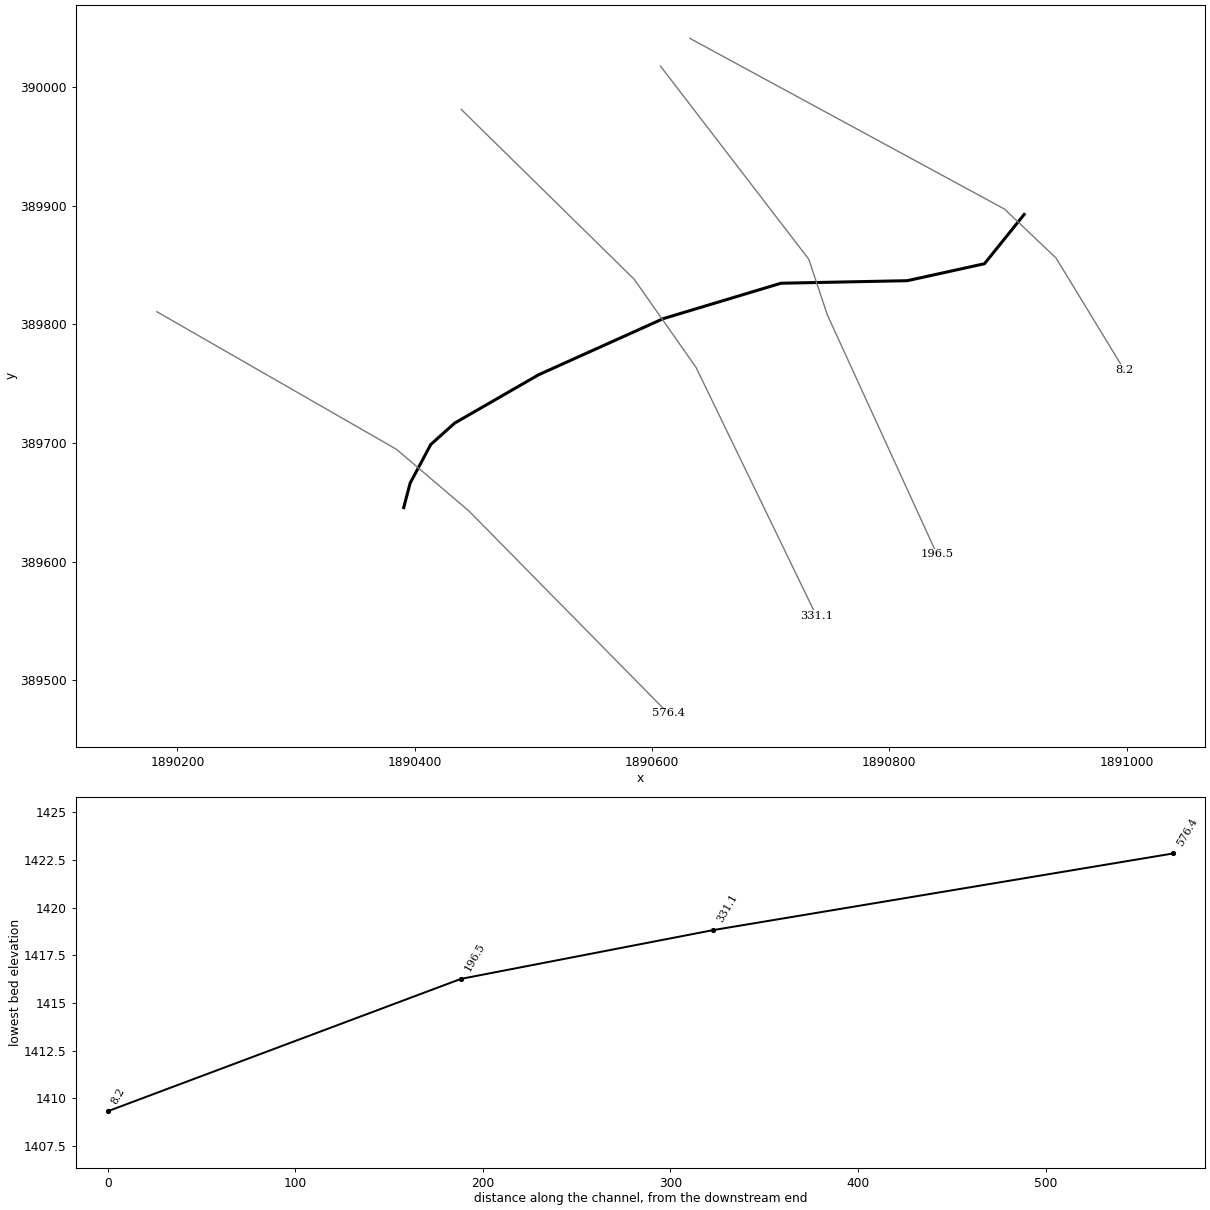
--- MOUNTRN.prj (project) ---

Proj Title=MOUNTRN
Current Plan=p01
Geom File=g01
Flow File=f01
Plan File=p01
DSS Export Rating Curves=0
DSS Export Rating Curve Sorted=0
DSS Export Volume Flow Curves=0
DXF OffsetX=0
DXF OffsetY=0
DXF ScaleX=0
DXF ScaleY=0

--- MOUNTRN.p01 (plan) ---

Plan Title=Floodplain
Program Version=4.00
Geom File=g01
Flow File=f01
K Sum by GR=0
Std Step Tol=0.01
Critical Tol=0.01
Num of Std Step Trials=20
Max Error Tol=0.3
Flow Tol Ratio=0.001
Split Flow NTrial=30
Split Flow Tol=0.02
Split Flow Ratio=0.02
Log Output Level=0
Friction Slope Method=1
Unsteady Friction Slope Method=2
Unsteady Bridges Friction Slope Method=1
Global Log Level=0
CheckData=False
Run HTab=0
Run UNet=0
Run PostProcess=0
UNET Theta=0
UNET Theta Warmup=0
UNET ZTol=0
UNET ZSATol=0
UNET MxIter=0
UNET MaxInSteps=0
UNET DtIC=0
UNET DtMin=0
UNET MaxCRTS=0
UNET WFStab=0
UNET SFStab=0
UNET WFX=0
UNET SFX=0
UNET DSS MLevel=0
UNET DZMax Abort=0
UNET Convert EG Bridges=0
UNET Use Existing IB Tables=0
UNET Froude Limit=0
UNET Froude Power=0
Write IC File=0
Echo Input=False
Echo Output=False
Write Detailed=0

--- MOUNTRN.f01 (steady flow) ---

Flow Title=NFF Regression Equation
Program Version=4.00
Number of Profiles=1
Profile Names=P100yr
River Rch & RM=MOUNTRN,Main      ,576.4
653.4231
Boundary for River Rch & Prof#=MOUNTRN,Main      ,1
Up Type=0
Dn Type=3
Dn Slope=0.023587

--- MOUNTRN.g01 (geometry) ---

Geom Title=USGS 10m DEM
Program Version=4.00

River Reach=MOUNTRN     ,Main
Reach XY= 10
     1890390.697      389645.546     1890396.123      389666.163
     1890413.484      389698.715     1890433.651      389716.789
     1890504.392      389757.518     1890609.552      389804.864
     1890708.753      389834.690     1890815.222      389836.833
     1890880.246      389851.124     1890913.714      389892.683

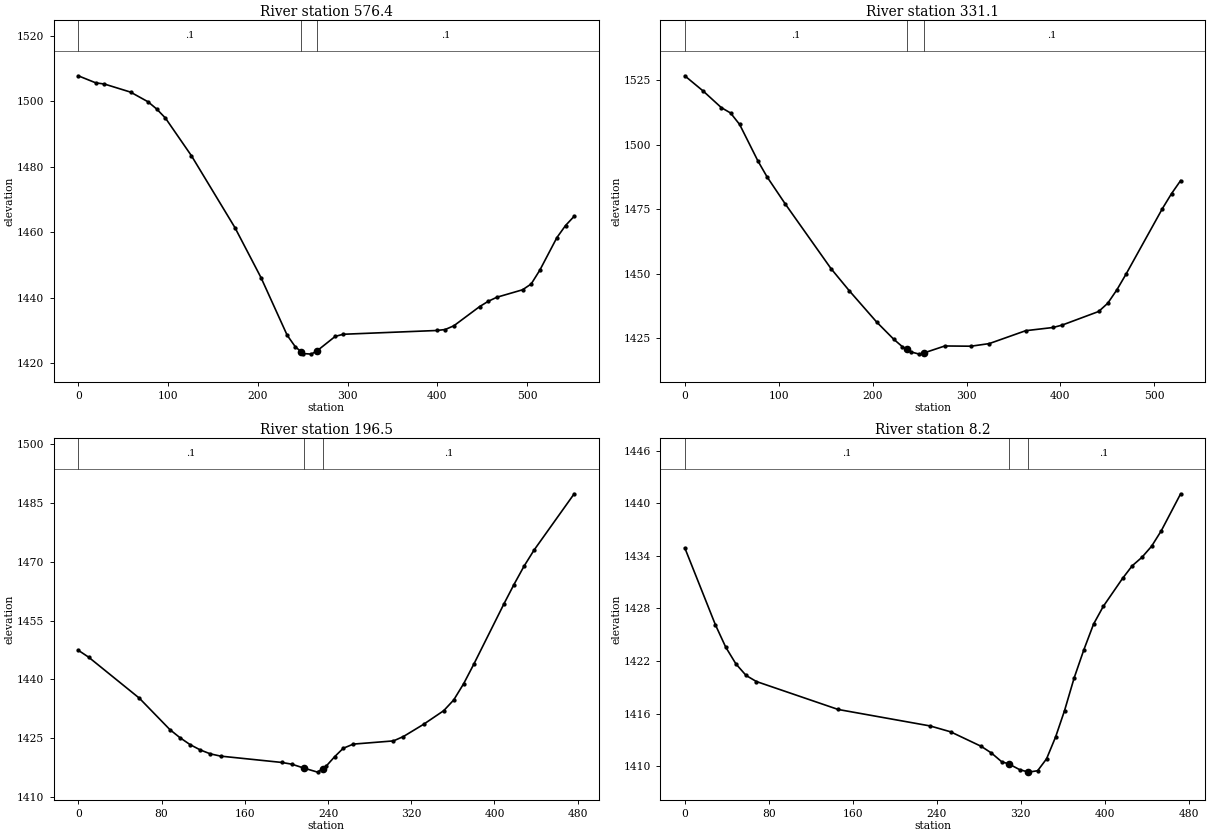
Type RM Length L Ch R = 1 ,576.4,251.4,245.3,239.4
XS GIS Cut Line= 4
     1890182.668      389810.651     1890384.491      389694.765
     1890445.689      389642.682     1890613.657      389472.109
#Sta/Elev= 30
       0 1507.75    19.4 1505.61    29.1 1505.24    58.2 1502.78    77.6 1499.84
    87.3 1497.63    97.0 1494.88   126.1 1483.34   174.6 1461.39   203.6 1446.16
   232.7 1428.61   241.7 1425.11     248 1423.63   250.6 1423.02   259.5 1422.84
     266 1423.84   286.3 1428.26   295.2 1428.90   399.3 1430.05   408.8 1430.35
   418.4 1431.48   447.2 1437.35   456.7 1438.95   466.3 1440.19   495.0 1442.47
   504.6 1444.24   514.2 1448.44   533.3 1458.41   542.9 1462.08   552.5 1464.90
#Mann= 3 , 0 , 0
       0     0.1       0     248   0.045       0     266     0.1       0
Bank Sta=248,266
Exp/Cntr=0.3,0.1

Type RM Length L Ch R = 1 ,331.1,139.6,134.6,127.6
XS GIS Cut Line= 4
     1890439.178      389981.223     1890585.012      389837.994
     1890637.095      389763.776     1890738.657      389554.140
#Sta/Elev= 30
       0 1526.66    19.5 1520.79    38.9 1514.34    48.7 1512.27    58.4 1507.81
    77.9 1493.64    87.6 1487.51   107.1 1476.95   155.7 1451.96   175.2 1443.36
   204.4 1431.22   222.5 1424.59   231.6 1421.73   236.4 1420.65   240.7 1419.69
   249.7 1418.82   254.4 1419.25   276.9 1421.98   304.8 1421.89   324.2 1422.90
   363.0 1427.90   392.1 1429.14   401.8 1430.07   440.7 1435.34   450.4 1438.54
   460.1 1443.73   469.8 1449.77   508.6 1475.22   518.3 1481.01   528.0 1486.07
#Mann= 3 , 0 , 0
       0     0.1       0   236.4   0.045       0   254.4     0.1       0
Bank Sta=236.4,254.4
Exp/Cntr=0.3,0.1

Type RM Length L Ch R = 1 ,196.5,175.7,188.3,200.5
XS GIS Cut Line= 4
     1890607.147      390017.682     1890732.147      389854.921
     1890747.772      389808.046     1890840.220      389606.223
#Sta/Elev= 30
       0 1447.39     9.8 1445.66    58.6 1435.17    88.0 1427.13    97.7 1425.06
   107.5 1423.28   117.3 1421.92   127.0 1420.92   136.8 1420.35   195.4 1418.74
   205.2 1418.29   216.9 1417.29   229.9 1416.26   234.9 1417.18   238.2 1417.78
   246.4 1420.21   254.6 1422.35   264.3 1423.42   302.9 1424.24   312.5 1425.36
   331.8 1428.47   351.2 1431.96   360.8 1434.69   370.4 1438.87   380.1 1443.82
   409.1 1459.26   418.7 1464.18   428.4 1468.88   438.0 1472.98   476.6 1487.38
#Mann= 3 , 0 , 0
       0     0.1       0   216.9   0.045       0   234.9     0.1       0
Bank Sta=216.9,234.9
Exp/Cntr=0.3,0.1

Type RM Length L Ch R = 1 ,8.2,8.4,8.2,10.1
XS GIS Cut Line= 4
     1890631.887      390041.119     1890897.199      389897.152
     1890940.602      389855.920     1890998.111      389761.519
#Sta/Elev= 30
       0 1434.91    29.2 1426.12    39.0 1423.58    48.7 1421.67    58.4 1420.35
    68.2 1419.66   146.1 1416.47   233.7 1414.59   253.2 1413.92   282.4 1412.26
   292.1 1411.50   301.9 1410.50   308.6 1410.26   319.0 1409.60   326.6 1409.35
   327.5 1409.32   336.1 1409.48   344.6 1410.84   353.2 1413.33   361.7 1416.33
   370.9 1420.08   380.2 1423.31   389.4 1426.22   398.6 1428.23   417.0 1431.43
   426.2 1432.87   435.4 1433.83   444.6 1435.09   453.8 1436.85   472.3 1441.08
#Mann= 3 , 0 , 0
       0     0.1       0   308.6   0.045       0   326.6     0.1       0
Bank Sta=308.6,326.6
Exp/Cntr=0.3,0.1